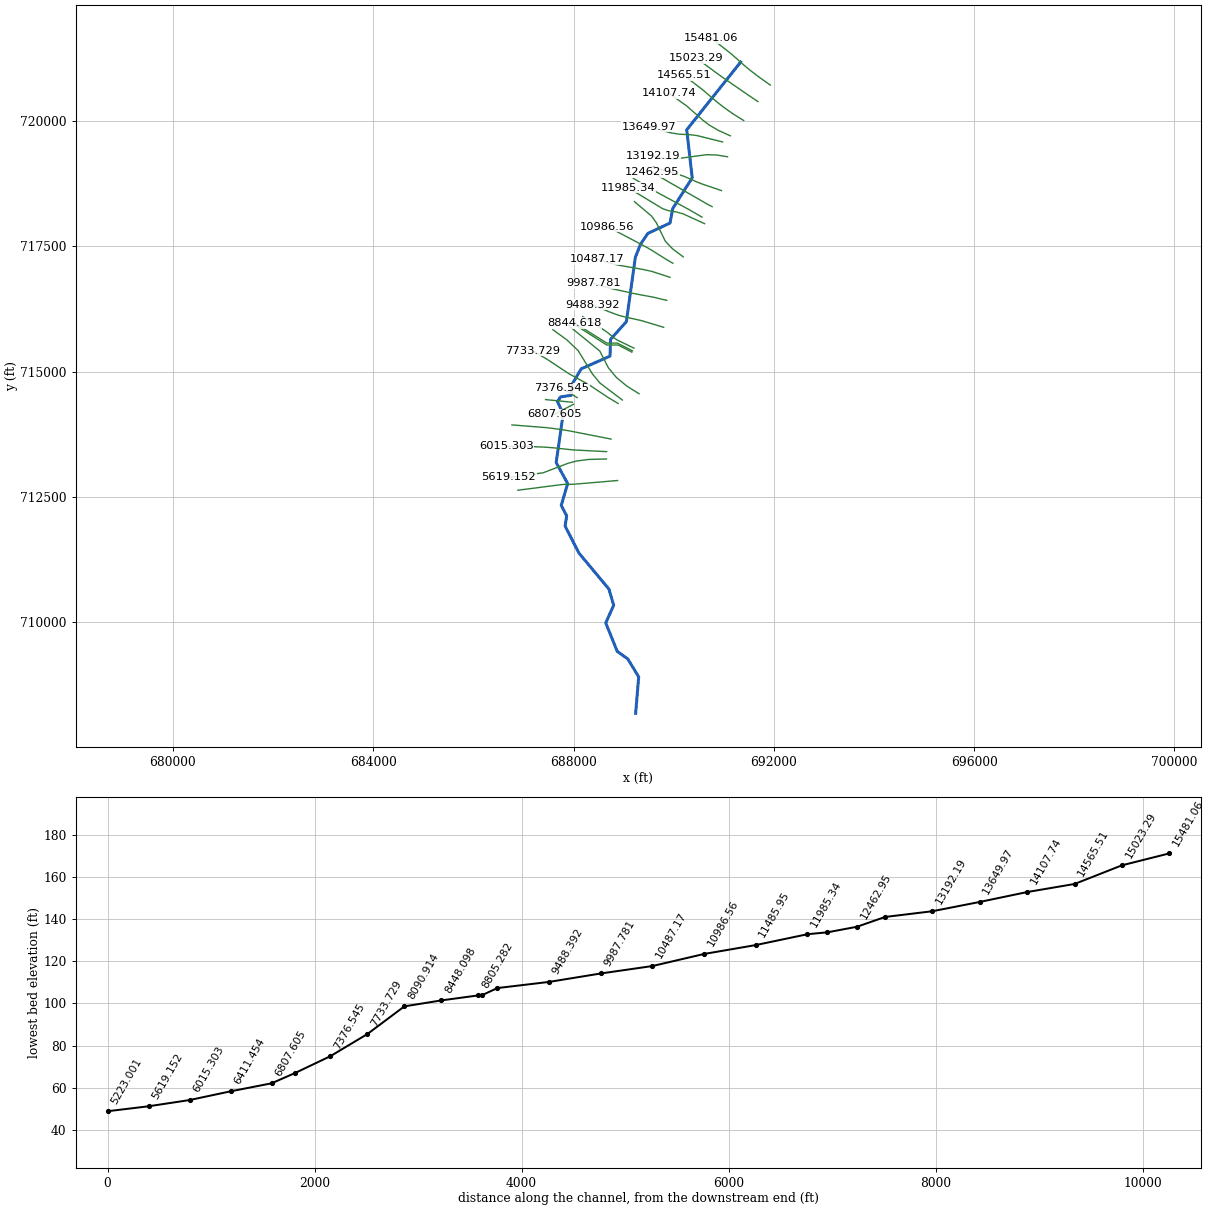
--- 5048_ras.prj (project) ---

Proj Title=5048
Current Plan=p01
Default Exp/Contr=0.3,0.1
English Units
Geom File=g01
Flow File=f01
Plan File=p01
Y Axis Title=Elevation
X Axis Title(PF)=Main Channel Distance
X Axis Title(XS)=Station
BEGIN DESCRIPTION:
RFD model 5048 exported to HEC-RAS
END DESCRIPTION:

--- 5048_ras.p01 (plan) ---

Plan Title=Plan 01
Program Version=4.10
Short Identifier=Plan 01
Geom File=g01
Flow File=f01
Subcritical Flow
Calc Critical at every XS
Secant Critical Depth

--- 5048_ras.f01 (steady flow) ---

Flow Title=Flow 01
Program Version=5.01
Number of Profiles= 6
Profile Names=10yr,25yr,50yr,100yr,100plus,500yr
River Rch & RM=5048,39,15481.06
 2989.83 5593.12 8383.27 11361.716588.0822365.08
River Rch & RM=5048,39,15023.29
 2994.59  5603.1 8399.3111384.7516621.74 22409.8
River Rch & RM=5048,39,14565.51
 3010.82 5637.24 8454.2111463.7116737.0222563.09
River Rch & RM=5048,39,14107.74
 3016.58 5649.46 8473.95 11492.216778.6222618.79
River Rch & RM=5048,39,13649.97
 3034.91  5688.6 8537.4411584.1516912.8622799.65
River Rch & RM=5048,39,13192.19
 3036.91  5692.9 8544.4311594.2816927.6422819.63
River Rch & RM=5048,39,12734.42
 3048.49 5717.83 8585.0411653.2817013.79 22936.4
River Rch & RM=5048,39,12462.95
  3055.6 5733.18 8610.0811689.72   1706723008.71
River Rch & RM=5048,39,12177.45
 3057.73 5737.81 8617.67 11700.817083.1723030.83
River Rch & RM=5048,39,11985.34
 3059.09 5740.77  8622.511707.8417093.4523044.83
River Rch & RM=5048,39,11485.95
  3061.2 5745.38 8630.0611718.8917109.5823066.94
River Rch & RM=5048,39,10986.56
 3067.62 5759.42 8653.1411752.6717158.8923134.68
River Rch & RM=5048,39,10487.17
 3070.87 5766.55 8664.8811769.86   1718423169.25
River Rch & RM=5048,39,9987.781
 3078.57  5783.5 8692.7911810.7717243.7323251.55
River Rch & RM=5048,39,9488.392
 3081.96 5790.98 8705.1511828.9317270.2423288.26
River Rch & RM=5048,39,8989.003
 3090.79 5810.59  8737.6 11876.717339.9823385.06
River Rch & RM=5048,39,8844.618
 3091.26 5811.63 8739.3211879.2317343.6823390.19
River Rch & RM=5048,39,8448.098
 3094.61 5819.12 8751.7611897.5817370.4723427.54
River Rch & RM=5048,39,8090.914
 3095.97 5822.17 8756.85 11905.117381.4523442.92
River Rch & RM=5048,39,7733.729
 3101.72 5835.09 8778.3711936.9317427.9223508.04
River Rch & RM=5048,39,7376.545
 3102.92 5837.82 8782.9211943.6917437.7923521.93
River Rch & RM=5048,39,7036.111
 3105.28 5843.15 8791.8211956.8717457.0323548.97
River Rch & RM=5048,39,6807.605
 3107.71 5848.62 8800.9611970.4117476.7923576.73
River Rch & RM=5048,39,6411.454
 3109.28 5852.19 8806.9411979.2817489.7523594.99
River Rch & RM=5048,39,6015.303
 3114.84 5864.79 8827.9912010.5117535.3523659.21
River Rch & RM=5048,39,5619.152
 3131.62 5903.05  8892.212106.0417674.8123856.55
River Rch & RM=5048,39,5223.001
 3132.65 5905.42  8896.212111.9917683.51 23868.9
River Rch & RM=5048,39, 4826.85
 3201.93 6057.75 9147.2912480.4918221.5224608.02
River Rch & RM=5048,39,4430.699
 3204.57 6063.76 9157.3712495.4918243.4224638.89
River Rch & RM=5048,39,4034.548
 3206.12 6067.33 9163.3912504.4818256.5524657.55
River Rch & RM=5048,39,3668.375
 3207.07 6069.51 9167.0912510.0118264.6224669.03
River Rch & RM=5048,39,3272.923
 3208.43 6072.66  9172.412517.9518276.2124685.53
River Rch & RM=5048,39,2949.401
 3224.57 6109.52 9234.3712610.3118411.0524876.05
River Rch & RM=5048,39,2542.152
 3225.76 6112.26 9238.99 12617.218421.1224890.35
River Rch & RM=5048,39,2284.806
 3226.17 6113.21 9240.5912619.6118424.6324895.36
River Rch & RM=5048,39,1855.421
  3237.2 6138.72 9283.7212684.18 18518.925029.63
River Rch & RM=5048,39, 949.438
 3365.02 6426.88 9765.3513399.1219562.7226486.39
River Rch & RM=5048,39,       0
 3367.15 6431.81 9773.68 13411.619580.9426512.21
Boundary for River Rch & Prof#=5048,39,1
Up Type= 0
Dn Type= 2
Boundary for River Rch & Prof#=5048,39,2
Up Type= 0
Dn Type= 2
Boundary for River Rch & Prof#=5048,39,2
Up Type= 0
Dn Type= 2
Boundary for River Rch & Prof#=5048,39,2
Up Type= 0
Dn Type= 2
Boundary for River Rch & Prof#=5048,39,2
Up Type= 0
Dn Type= 2
Boundary for River Rch & Prof#=5048,39,2
Up Type= 0
Dn Type= 2

--- 5048_ras.g01 (geometry) ---

Geom Title=5048
Program Version=4.10

River Reach=5048,39
Reach XY= 30
691337.341037989721182.274570242690260.778537989719829.670403585
690370.153537959718871.857903585689982.653537989718258.316236928
689926.403537989  717967.1704036689485.778537989717761.441236913
689336.299371302717540.607903585689234.736871272717283.837070256
689055.570204616715998.941236928688740.466037989 715646.85790357
688729.007704645715310.399570242688154.007704616715056.753736913
687960.257704616714729.149570256687956.091037929 714528.10790357
687742.028537989714496.337070242687680.049371272714404.149570242
687793.591037959714155.712070242687653.486871302713184.878736913
687883.695204645712765.607903585687754.528537989 712329.67040357
687863.382704616 712120.29540357687831.611871302711917.691236913
688106.611871302711380.191236928688707.653537959710657.274570242
688802.445204616710335.920403585688643.591037989 709982.79540357
688873.278537959709413.524570256689083.695204616709264.045403585
689301.403537989708905.191236928689240.640949517708176.479767948

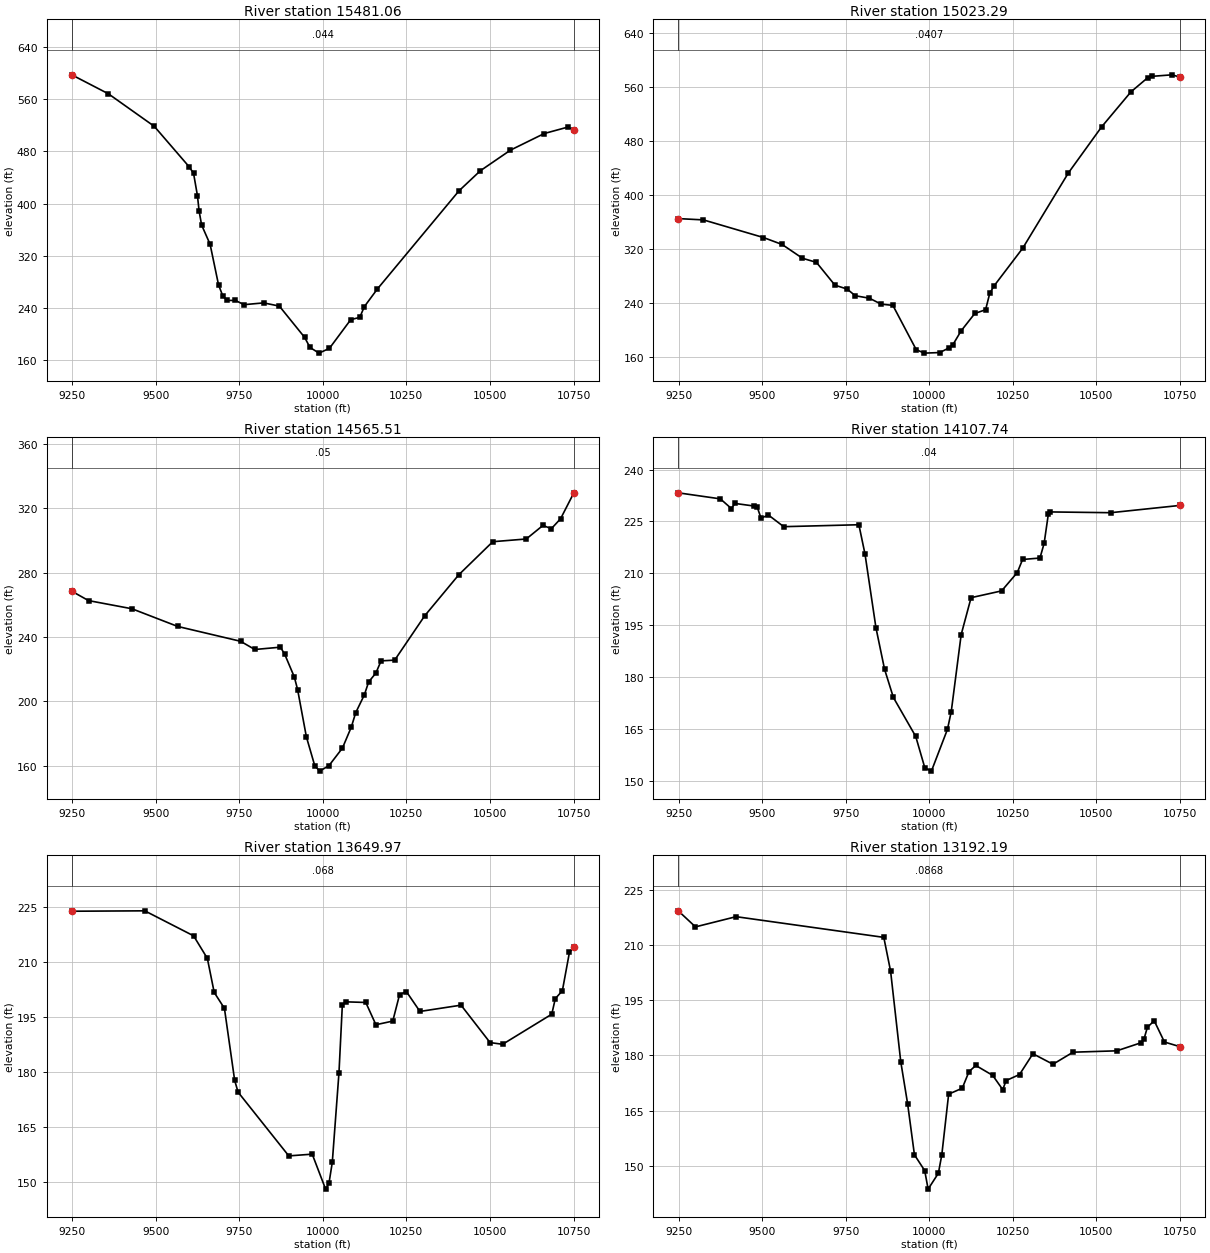
Type RM Length L Ch R = 1 ,15481.06,457.773300,457.773300,457.773300
XS GIS Cut Line= 6
691930.063741827720722.377212464691712.274385481720876.811717568
 691525.15210677721019.191424991691415.263691493721110.275337298
 691150.16615164721345.564150963690754.883327431721655.924156022
#Sta/Elev= 30
9249.025597.24699358.685568.16329495.779518.38999599.957456.53179613.322 446.451
9624.911412.43489630.043388.36069637.406367.26549662.805337.7684 9688.05275.6581
9700.711258.76069713.372251.78579738.694251.72629764.348 245.2649822.945247.9865
9869.955243.0921  9945.6195.16279961.728179.7171 9988.72171.050310019.92178.4339
10083.57222.314710110.54225.778310124.32242.292110163.14269.204310407.26419.5249
10471.17450.304110561.48481.946510662.47507.358610733.08517.216910750.98512.9795
#Mann= 3 , 0 , 0
9249.025   0.044       09249.025   0.044       010750.98   0.044       0
#XS Ineff= 2 , 0
       0                               0
Bank Sta=9249.025,10750.98
Exp/Cntr=0.3,0.1

Type RM Length L Ch R = 1 ,15023.29,457.773300,457.773300,457.773300
XS GIS Cut Line= 6
691682.752653151720392.973069818691461.058509732720541.755919352
691063.703312251720816.344794403690936.007319952720905.777498258
690767.811029739721027.618213135690456.572247411721259.975644381
#Sta/Elev= 30
9249.007364.84819324.425362.92399503.875336.79689559.829326.46999620.606306.0535
9662.425299.9647 9717.85266.12329754.316260.37919778.627250.49289820.735246.8455
9855.915238.06089891.095236.20649960.958 170.5319985.268165.407510031.51166.2626
10058.46173.016510070.67177.888810095.09198.296110136.11224.157710168.49229.7835
10180.84253.855410193.19264.674810279.62321.017210416.01432.461210515.85501.0234
10603.21552.685710653.12573.5957 10665.6575.729810725.96577.9979   10751  574.51
#Mann= 3 , 0 , 0
9249.007  0.0407       09249.007  0.0407       0   10751  0.0407       0
#XS Ineff= 2 , 0
       0                               0
Bank Sta=9249.007,10751
Exp/Cntr=0.3,0.1

Type RM Length L Ch R = 1 ,14565.51,457.773300,457.773300,457.773300
XS GIS Cut Line= 6
691397.954195935720014.621696507691171.862177511720156.568025979
690980.624490816720293.340341993690854.428498822720393.272502742
690580.010968227720627.860469745690201.090746916720918.751703912
#Sta/Elev= 30
9249.035268.39129299.187262.56129428.991 257.4869565.885246.49579753.834 237.277
9796.602 232.1639873.136233.60579885.892229.28939914.785215.07019924.556207.2911
9950.909177.83939975.764160.03829990.479156.561810018.36159.964810058.71170.8793
 10085.4184.015210098.36192.855710124.27203.963210137.22 212.04910158.64217.4688
10174.37225.097410214.96225.541910305.04253.168410406.73278.595610508.43299.1663
10608.64300.853110658.62309.295110683.61307.230510711.36313.462310750.97329.5447
#Mann= 3 , 0 , 0
9249.035    0.05       09249.035    0.05       010750.97    0.05       0
#XS Ineff= 2 , 0
       0                               0
Bank Sta=9249.035,10750.97
Exp/Cntr=0.3,0.1

Type RM Length L Ch R = 1 ,14107.74,457.773200,457.773200,457.773200
XS GIS Cut Line= 6
691130.242616416719709.396490225690887.587772298719820.658100661
690706.155089666719926.837523418690590.629542981720015.107215559
690259.092924575720306.541282364689902.595499639720560.155556353
#Sta/Elev= 30
9249.062233.2861 9375.07231.53959407.873228.74719418.876230.21629474.459229.4811
9485.576229.08179496.692225.9693    9519226.84859564.618 223.4899789.434224.0495
9807.778215.55129840.552194.20079866.208182.24079892.595174.06159959.505162.7717
9986.687153.700610006.39152.736710054.44164.842510065.74169.961810095.41192.2411
10125.08202.938210216.39204.904510263.27210.205810279.15213.996910331.13214.4129
 10343.6218.668410356.37 227.24510359.99227.760510542.63227.533110750.97229.6515
#Mann= 3 , 0 , 0
9249.062    0.04       09249.062    0.04       010750.97    0.04       0
#XS Ineff= 2 , 0
       0                               0
Bank Sta=9249.062,10750.97
Exp/Cntr=0.3,0.1

Type RM Length L Ch R = 1 ,13649.97,457.773300,457.773300,457.773300
XS GIS Cut Line= 6
690977.307851265719586.869579659690468.361605922 719713.48551349
 690339.81971467 719730.86211028690115.167140505719741.050898453
689923.371955081719772.049994647689512.502703041719891.533195673
#Sta/Elev= 30
9249.034223.92479467.396224.03439613.487 217.2069654.595211.05289675.105201.7547
9705.711197.40449736.316177.74589746.518 174.5299898.237157.12079968.337157.5998
10008.34148.050110018.35 149.60610028.35 155.36410048.35179.828610058.37198.2503
 10068.4199.189910128.57199.013110158.84192.935210209.29193.932610229.53201.1339
10249.88201.997710290.58 196.56310413.51198.278710500.36188.061210537.91187.5964
10684.91195.813110695.48200.067610716.61202.214310737.74212.687510750.95214.0687
#Mann= 3 , 0 , 0
9249.034   0.068       09249.034   0.068       010750.95   0.068       0
#XS Ineff= 2 , 0
       0                               0
Bank Sta=9249.034,10750.95
Exp/Cntr=0.3,0.1

Type RM Length L Ch R = 1 ,13192.19,457.773300,457.773300,457.773300
XS GIS Cut Line= 6
691075.687895635719291.604740616690859.768512859719325.716837605
690658.637579243719332.901528934690004.138477092719244.154198552
689805.719253779719257.587239755689588.613960209719298.819328228
#Sta/Elev= 30
9249.089219.33879300.648214.97369422.146217.74829863.966212.12069884.286202.9322
9914.766178.26669935.145166.91059955.616  152.989986.323148.68499996.559143.6456
10027.25147.977410037.48152.981810057.94 169.48110098.63171.093310118.92 175.625
 10139.2177.275310189.61174.594810219.78170.702610229.83173.168910269.95174.8174
10309.98180.466710370.02 177.61410430.06180.889910560.95181.263310631.86183.4096
10642.05184.387110652.28187.624410672.75189.457810703.44183.6543 10750.9182.3618
#Mann= 3 , 0 , 0
9249.089  0.0868       09249.089  0.0868       0 10750.9  0.0868       0
#XS Ineff= 2 , 0
       0                               0
Bank Sta=9249.089,10750.9
Exp/Cntr=0.3,0.1

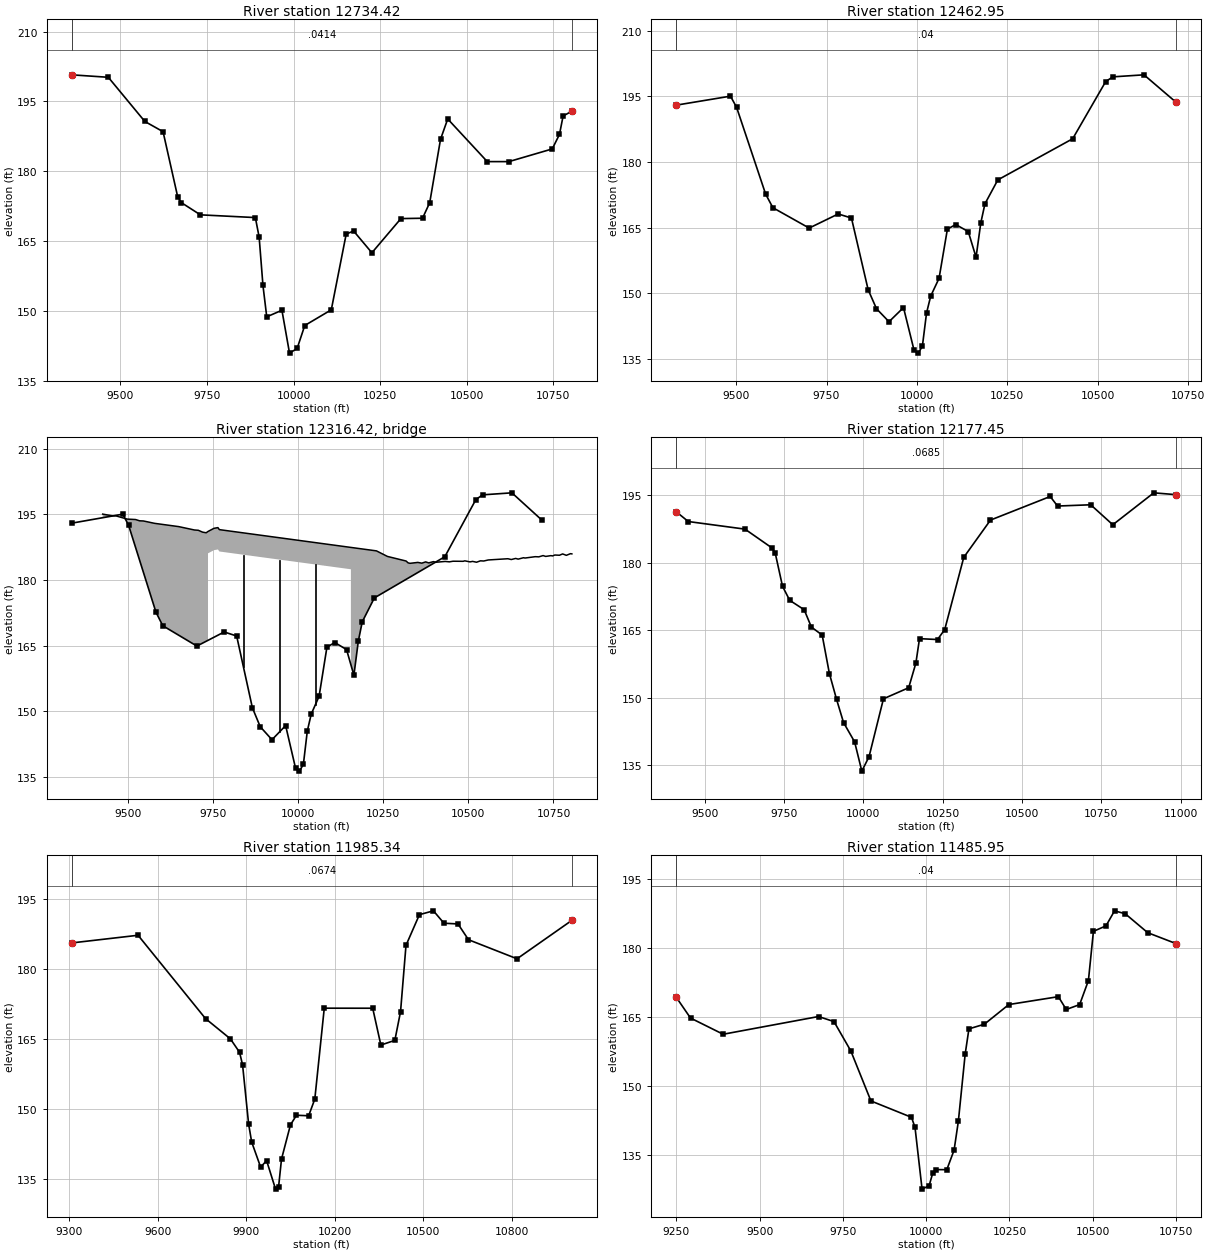
Type RM Length L Ch R = 1 ,12734.42,271.469100,271.469100,271.469100
XS GIS Cut Line= 6
690955.344218165718615.521358401690566.389437467718747.997851476
690454.263137311718792.076852009  690198.1864371718904.373813719
 690045.78160888718953.250665605689590.736706883719085.108459875
#Sta/Elev= 30
9359.186200.70069464.993200.17099570.437190.68979623.159188.48749665.533174.4602
9676.136173.2423 9731.01170.62569889.782170.03879900.732165.83839911.699155.4865
9922.666148.72139966.532150.13059988.465 140.92310010.45141.9235 10032.5146.8562
10109.16150.230210152.18166.503510173.63167.151810226.41 162.47910310.25169.8205
10372.71169.896410393.48173.247110424.65186.847210445.43191.2203 10559.7182.0597
10622.08182.058210747.44184.784310768.33187.920610778.78191.861910804.12192.8803
#Mann= 3 , 0 , 0
9359.186  0.0414       09359.186  0.0414       010804.12  0.0414       0
#XS Ineff= 2 , 0
       0                               0
Bank Sta=9359.186,10804.12
Exp/Cntr=0.3,0.1

Type RM Length L Ch R = 1 ,12462.95,285.506400,285.506400,285.506400
XS GIS Cut Line= 4
690767.567372918718295.680674791690707.910294652718324.631903961
689873.650008529718804.260218859 689568.02104038718983.920490682
#Sta/Elev= 30
9333.944193.00639484.356195.06819501.312192.50249581.566172.6549 9601.63169.5468
9701.948164.88879782.202168.11569818.867167.18979865.006150.78559888.076146.4424
 9922.68143.46219962.774146.69849991.889136.964110003.42136.278510014.96137.8414
10026.49 145.46110038.03149.3333 10061.1 153.39910084.17 164.65110107.24165.6947
10141.84  164.0910163.41158.214610176.45 166.04610187.98170.4417 10223.6175.9114
10430.59185.322210521.89 198.40810541.62199.485910627.79199.948810717.09193.6243
#Mann= 3 , 0 , 0
9333.944    0.04       09333.944    0.04       010717.09    0.04       0
#XS Ineff= 2 , 0
       0                               0
Bank Sta=9333.944,10717.09
Exp/Cntr=0.3,0.1

Type RM Length L Ch R = 3 ,12316.42,,,
BEGIN DESCRIPTION:
END DESCRIPTION:
Bridge Culvert--1,0,-1,-1, 0
Deck Dist Width WeirC Skew NumUp NumDn MinLoCord MaxHiCord MaxSubmerge Is_Ogee
102.753200,80.000000,2.6,0, 60, 60, , , 0.95, 0, 0,0,,
 9425.04 9452.65 9464.18 9497.05 9521.79 9533.31 9544.83 9577.57 9648.54 9694.63
 9706.15 9718.47 9729.19 9734.62 9734.62 9752.24 9763.76 9767.9810154.6210154.62
10229.7210261.9610316.7610322.6310328.2610351.2710363.0810374.2810383.3010397.29
10403.5310431.8010443.9810454.8110484.4310489.3310504.6510512.3410523.8410535.35
10545.1010558.3510615.8810626.0010638.8910646.2210661.9010666.4510696.4110706.90
10719.4210727.1210742.4310747.3510753.9310767.5710776.9410787.8010799.9510804.09
  195.08  194.70  194.67  193.94  193.84  193.55  193.51  192.97  192.22  191.45
  191.38  190.96  190.81  191.11  191.11  191.83  191.99  191.53  187.46  187.46
  186.67  185.40  184.35  183.93  183.82  184.03  183.86  184.15  183.92  184.21
  184.06  184.25  184.16  184.30  184.28  184.39  184.15  184.26  184.07  184.39
  184.35  184.59  184.87  184.69  184.94  184.78  185.10  185.03  185.34  185.30
  185.59  185.40  185.58  185.51  185.72  185.67  185.97  185.65  186.03  185.98
 -804.92 -805.30 -805.33 -806.06 -806.16 -806.45 -806.49 -807.03 -807.78 -808.55
 -808.62 -809.04 -809.19 -808.89  186.11  186.83  186.99  186.53  182.46 -812.54
 -813.33 -814.60 -815.65 -816.07 -816.18 -815.97 -816.14 -815.85 -816.08 -815.79
 -815.94 -815.75 -815.84 -815.70 -815.72 -815.61 -815.85 -815.74 -815.93 -815.61
 -815.65 -815.41 -815.13 -815.31 -815.06 -815.22 -814.90 -814.97 -814.66 -814.70
 -814.41 -814.60 -814.42 -814.49 -814.28 -814.33 -814.03 -814.35 -813.97 -814.02
 9425.04 9452.65 9464.18 9497.05 9521.79 9533.31 9544.83 9577.57 9648.54 9694.63
 9706.15 9718.47 9729.19 9738.60 9752.24 9763.76 9767.98 9845.53 9845.5310229.72
10265.5310265.5310316.7610322.6310328.2610351.2710363.0810374.2810383.3010397.29
10403.5310431.8010443.9810454.8110484.4310489.3310504.6510512.3410523.8410535.35
10545.1010558.3510615.8810626.0010638.8910646.2210661.9010666.4510696.4110706.90
10719.4210727.1210742.4310747.3510753.9310767.5710776.9410787.8010799.9510804.09
  195.08  194.70  194.67  193.94  193.84  193.55  193.51  192.97  192.22  191.45
  191.38  190.96  190.81  191.34  191.83  191.99  191.53  190.72  190.72  186.67
  185.30  185.30  184.35  183.93  183.82  184.03  183.86  184.15  183.92  184.21
  184.06  184.25  184.16  184.30  184.28  184.39  184.15  184.26  184.07  184.39
  184.35  184.59  184.87  184.69  184.94  184.78  185.10  185.03  185.34  185.30
  185.59  185.40  185.58  185.51  185.72  185.67  185.97  185.65  186.03  185.98
 -804.92 -805.30 -805.33 -806.06 -806.16 -806.45 -806.49 -807.03 -807.78 -808.55
 -808.62 -809.04 -809.19 -808.66 -808.17 -808.01 -808.47 -809.28  185.72  181.67
  180.30 -814.70 -815.65 -816.07 -816.18 -815.97 -816.14 -815.85 -816.08 -815.79
 -815.94 -815.75 -815.84 -815.70 -815.72 -815.61 -815.85 -815.74 -815.93 -815.61
 -815.65 -815.41 -815.13 -815.31 -815.06 -815.22 -814.90 -814.97 -814.66 -814.70
 -814.41 -814.60 -814.42 -814.49 -814.28 -814.33 -814.03 -814.35 -813.97 -814.02
Pier Skew, UpSta & Num, DnSta & Num=  ,9838.87, 2 ,9949.78, 2 , 0 , 0 , 0 ,,
    3.00    3.00
 -809.21  190.79
    3.00    3.00
 -810.38  189.62
Pier Skew, UpSta & Num, DnSta & Num=  ,9944.62, 2 ,10055.53, 2 , 0 , 0 , 0 ,,
    3.00    3.00
 -810.33  189.67
    3.00    3.00
 -811.50  188.50
Pier Skew, UpSta & Num, DnSta & Num=  ,10050.37, 2 ,10161.28, 2 , 0 , 0 , 0 ,,
    3.00    3.00
 -811.44  188.56
    3.00    3.00
 -812.61  187.39
BR Coef=-1 , 0 , 0 ,, 0 ,,,0.8,0,1,0,
WSPro=,,,, 1 ,,,, 0 ,,,, 0 ,,,,-1 ,-1 ,-1 , 0 , 0 , 0 , 0 , 0
BC Design=,, 0 ,, 0 ,,,,,,

Type RM Length L Ch R = 1 ,12177.45,192.108100,192.108100,192.108100
XS GIS Cut Line= 4
690565.445308089 718085.61913152690303.182612449718238.433615625
689652.688524812718589.493916899689192.655986071718861.067862287
#Sta/Elev= 30
9409.357  191.369447.854189.16179626.621187.47059712.893183.22749722.191182.0554
9744.918174.74859767.645 171.6319813.098169.55399835.825165.69369869.915163.9071
9892.642155.35979915.368149.58599937.275144.45049972.185140.15629994.912133.6475
10017.64136.854910063.09149.734210142.64152.193610165.36157.691810176.73  163.11
10233.54162.917710256.27 165.13910316.28181.1976 10400.5189.483410588.74194.7315
10611.96 192.60710716.48192.887410786.15188.446310915.34195.545710986.28195.1318
#Mann= 3 , 0 , 0
9409.357  0.0685       09409.357  0.0685       010986.28  0.0685       0
#XS Ineff= 2 , 0
       0                               0
Bank Sta=9409.357,10986.28
Exp/Cntr=0.3,0.1

Type RM Length L Ch R = 1 ,11985.34,499.389000,499.389000,499.389000
XS GIS Cut Line= 6
690617.230323855717955.444195424690184.208181361718152.798102947
690046.569126738718190.725143192689888.071851327718216.705364694
689777.044115497718255.991867405689094.224733096718669.884082525
#Sta/Elev= 30
9308.206185.53419533.317187.17669762.062169.31539846.402164.97359877.499162.0972
9887.764159.38979908.294146.70919918.558 142.8679949.029137.47069969.258138.8588
  9999.6132.751510009.71133.124110019.82139.188810050.22146.5403 10070.6148.5867
 10111.9148.481910132.74152.058910164.82171.543110329.12 171.53510356.76163.6411
10404.19164.646310423.53 170.81210441.98185.007410487.48191.594210535.08192.4166
10570.78189.756110618.37189.606610653.86186.223210818.59182.135411004.59190.3753
#Mann= 3 , 0 , 0
9308.206  0.0674       09308.206  0.0674       011004.59  0.0674       0
#XS Ineff= 2 , 0
       0                               0
Bank Sta=9308.206,11004.59
Exp/Cntr=0.3,0.1

Type RM Length L Ch R = 1 ,11485.95,499.389100,499.389100,499.389100
XS GIS Cut Line= 6
690190.685071392 717292.57124525689977.368480683717452.768526536
689832.869296628717605.209428672689652.388480206717976.169437135
689559.891955824718105.405900507 689215.94230518718395.273608911
#Sta/Elev= 30
9249.126169.41079292.408 164.8419390.445161.31169676.729165.16789723.125 164.068
9773.733 157.6819834.064146.79979955.877143.23749966.453141.05019987.604  127.61
10008.77 128.35410019.39131.029910030.01131.8603 10061.9131.842210083.75136.1008
10096.54142.354610117.09157.030210128.33162.484210174.58163.493610248.15167.7777
10396.85169.490110420.51166.6985 10460.7167.765610487.03172.988610502.07183.7055
10539.83184.898610565.47188.168810597.58 187.53410665.04183.412410750.87181.0149
#Mann= 3 , 0 , 0
9249.126    0.04       09249.126    0.04       010750.87    0.04       0
#XS Ineff= 2 , 0
       0                               0
Bank Sta=9249.126,10750.87
Exp/Cntr=0.3,0.1

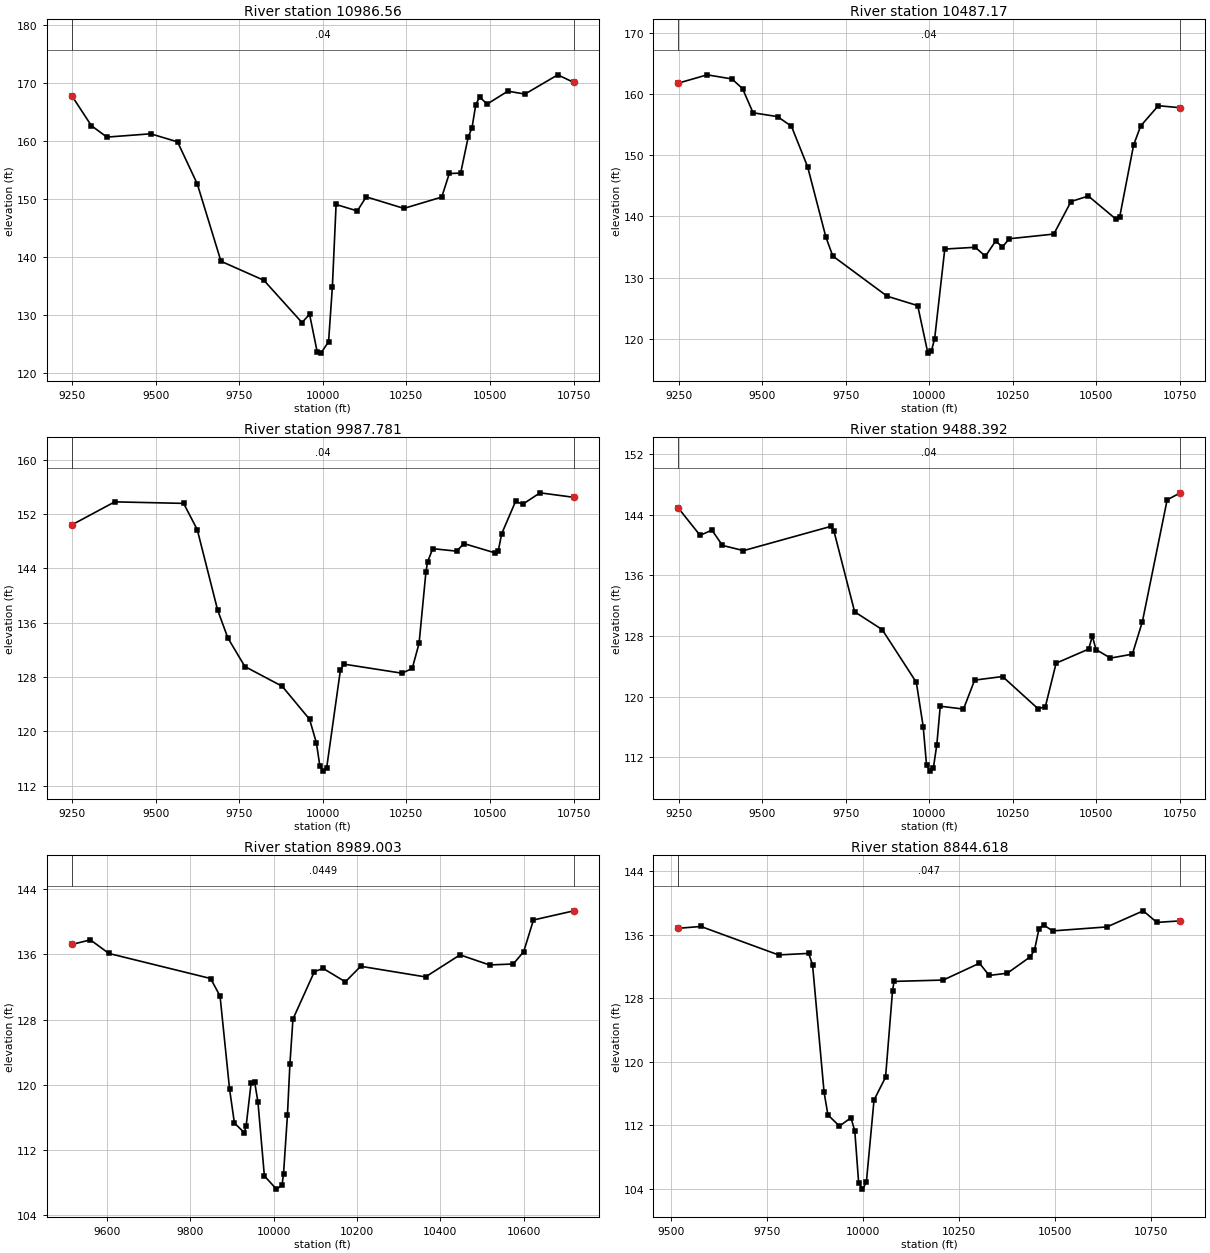
Type RM Length L Ch R = 1 ,10986.56,499.389000,499.389000,499.389000
XS GIS Cut Line= 6
689985.561053977717163.843653291689841.941893806717248.028263203
689578.721538581717413.426336454689476.664618209717474.106440724
689324.169128762717555.955773447688675.850115618717897.536238228
#Sta/Elev= 30
9249.032167.76429307.639162.59979354.004160.62479484.995161.19479565.428159.8085
 9624.48152.55919695.342139.2278 9823.78135.94159937.717 128.6639960.397130.0886
9983.077123.65059994.416123.392610017.24125.348610028.51134.705210039.77149.0095
10103.19147.899910129.83150.325510242.56148.337610355.76150.2844 10378.4154.3555
10412.36154.4154   10435160.638410446.32162.231910457.64166.212210468.96167.5376
 10491.6166.317410553.52168.5436 10604.8168.0419 10702.9171.359110750.99170.0403
#Mann= 3 , 0 , 0
9249.032    0.04       09249.032    0.04       010750.99    0.04       0
#XS Ineff= 2 , 0
       0                               0
Bank Sta=9249.032,10750.99
Exp/Cntr=0.3,0.1

Type RM Length L Ch R = 1 ,10487.17,499.389000,499.389000,499.389000
XS GIS Cut Line= 6
689926.350333752 716884.39900821689558.206209658717003.491387439
689385.676334789717041.336430264688885.318297875717128.150782782
688704.572330698717174.830475554 688472.43943999717248.479905683
#Sta/Elev= 30
9249.025161.78489335.601163.14679409.633162.47049441.286160.9013 9472.89156.9462
9546.057156.31649587.631154.74929636.129148.10879690.818  136.619711.376133.5382
9874.239126.96319965.386125.43279995.768117.670310005.89117.950210016.02120.0035
 10046.4134.676310137.54134.968810167.99133.499610198.52135.995510218.87135.0267
10239.22136.359210372.54137.124610424.04142.443410475.87143.341310559.17139.5319
10569.61139.905110611.38151.696510632.44154.7937 10685.1158.097310750.98157.7716
#Mann= 3 , 0 , 0
9249.025    0.04       09249.025    0.04       010750.98    0.04       0
#XS Ineff= 2 , 0
       0                               0
Bank Sta=9249.025,10750.98
Exp/Cntr=0.3,0.1

Type RM Length L Ch R = 1 ,9987.781,499.389100,499.389100,499.389100
XS GIS Cut Line= 6
689861.006631191716423.480043854689601.358998601716485.529384086
689220.543819549716556.802725106688770.886763299716655.821771489
688608.908912138716697.372320393688398.948926739716762.578188989
#Sta/Elev= 30
9249.022150.41959377.615153.81699583.633153.59099624.395149.72449685.421137.8596
 9715.92133.76779766.752129.55389878.581126.63779960.335121.7861 9980.82 118.302
9991.062114.936510001.31114.139310011.55114.6181 10052.5 128.97710062.74129.9054
 10236.8128.568810267.52129.271410287.99132.975510308.47143.470610313.46 144.986
10328.95  146.9210400.81146.549110421.57 147.67710514.49146.308110524.81146.5964
10535.17 149.12710576.88 153.91310597.73153.458710649.95 155.14710750.97154.4832
#Mann= 3 , 0 , 0
9249.022    0.04       09249.022    0.04       010750.97    0.04       0
#XS Ineff= 2 , 0
       0                               0
Bank Sta=9249.022,10750.97
Exp/Cntr=0.3,0.1

Type RM Length L Ch R = 1 ,9488.392,499.389000,499.389000,499.389000
XS GIS Cut Line= 6
 689801.05974426715885.287186721 689355.76436396716019.561721387
 688991.15924655 716101.17090395688895.369080249716127.427583611
688698.046959206716200.478034114688373.880078672716340.951270772
#Sta/Elev= 30
9249.032144.91999314.446141.29349349.775141.99369381.238139.96869444.163139.2751
9704.573142.46729714.965141.83139776.759131.1904 9859.15128.8439 9961.32121.8699
9981.746116.03299991.959110.890310002.16110.142610012.38110.5909 10022.6113.6532
10032.83118.721810102.35118.342610135.73122.168810219.29122.641110325.78118.3704
10347.25118.666510379.45124.405310476.94126.2728 10487.8127.999310498.65126.2048
10542.07 125.07910607.52125.5969 10637.6129.9123 10711.6145.985910750.95146.9148
#Mann= 3 , 0 , 0
9249.032    0.04       09249.032    0.04       010750.95    0.04       0
#XS Ineff= 2 , 0
       0                               0
Bank Sta=9249.032,10750.95
Exp/Cntr=0.3,0.1

Type RM Length L Ch R = 1 ,8989.003,144.385200,144.385200,144.385200
XS GIS Cut Line= 6
 689205.38062661715470.199399173688864.782339702715636.300213767
688806.057434682715677.142035121688683.459526017715778.885755667
 688605.42916888715834.085978021688181.938746003716100.314367026
#Sta/Elev= 30
9514.926137.21619559.712137.77659604.075136.11279848.416 133.0429871.039130.8843
9893.908 119.4859905.514115.32639929.242114.14869933.742114.99189945.634120.2192
9954.213120.32659962.003117.92619977.492108.849510006.51 107.22910019.72107.6754
 10023.5109.105910032.92 116.32810038.81 122.55310046.13128.068810097.58133.8805
10118.55134.281610171.99132.633910208.74134.539610364.57133.236310447.34135.9391
10518.28134.702510575.37134.8213 10600.3136.338310623.73140.214310720.74141.3368
#Mann= 3 , 0 , 0
9514.926  0.0449       09514.926  0.0449       010720.74  0.0449       0
#XS Ineff= 2 , 0
       0                               0
Bank Sta=9514.926,10720.74
Exp/Cntr=0.3,0.1

Type RM Length L Ch R = 1 ,8844.618,39.335500,39.335500,39.335500
XS GIS Cut Line= 4
689177.445790735715415.799981938688876.559578449715569.896231934
688666.490133971715569.896231934688023.195787854715972.206014838
#Sta/Elev= 30
9519.681136.78999578.605 137.0219780.838133.43449859.291133.62859869.291132.1847
9899.291116.14229909.291113.27819939.291111.86969969.291112.91799979.291111.2281
9989.291104.72089999.291103.928110009.29104.765410029.29115.147910059.29118.0244
10077.43 128.87510081.35130.098610209.44130.268610303.74132.388910329.04130.8506
10376.22131.130910435.76133.187610446.98134.045810458.78136.751610470.57137.2245
10494.16136.4607 10635.7136.965610730.05138.991510765.44137.534510826.54137.7236
#Mann= 3 , 0 , 0
9519.681   0.047       09519.681   0.047       010826.54   0.047       0
#XS Ineff= 2 , 0
       0                               0
Bank Sta=9519.681,10826.54
Exp/Cntr=0.3,0.1

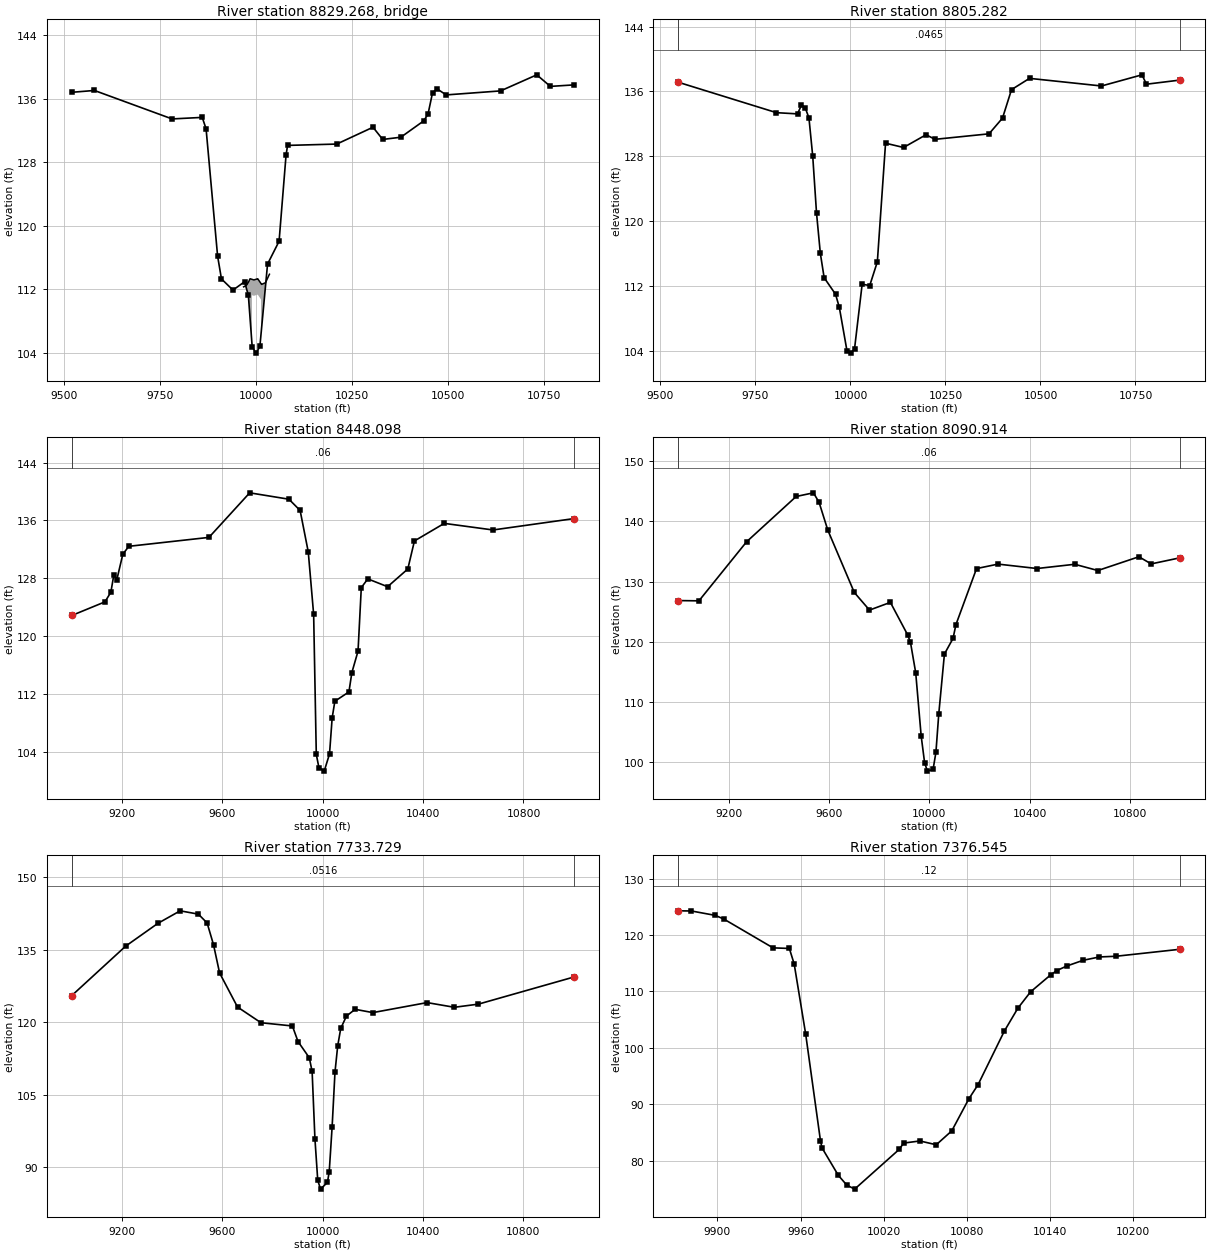
Type RM Length L Ch R = 3 ,8829.268,,,
BEGIN DESCRIPTION:
END DESCRIPTION:
Bridge Culvert--1,0,-1,-1, 0
Deck Dist Width WeirC Skew NumUp NumDn MinLoCord MaxHiCord MaxSubmerge Is_Ogee
11.667750,16.000000,2.6,0, 16, 16, , , 0.95, 0, 0,0,,
 9966.94 9973.45 9979.91 9983.73 9988.49 9988.49 9993.7410003.7610003.8410012.32
10012.3210013.7710013.8010023.9210034.0610034.19
  112.28  112.42  112.90  113.30  113.23  113.23  113.15  113.30  113.29  112.69
  112.69  112.59  112.59  112.80  113.86  113.87
 -887.72 -887.58 -887.10 -886.70 -886.77  111.23  111.15  111.30  111.29  110.69
 -887.31 -887.41 -887.41 -887.20 -886.14 -886.13
 9966.94 9973.45 9979.91 9983.73 9989.01 9989.01 9993.7410003.7610003.8410012.10
10012.1010013.7710013.8010023.9210034.0610034.19
  112.28  112.42  112.90  113.30  113.22  113.22  113.15  113.30  113.29  112.71
  112.71  112.59  112.59  112.80  113.86  113.87
 -887.72 -887.58 -887.10 -886.70 -886.78  111.22  111.15  111.30  111.29  110.71
 -887.29 -887.41 -887.41 -887.20 -886.14 -886.13
BR Coef=-1 , 0 , 0 ,, 0 ,,,0.8,0,1,0,
WSPro=,,,, 1 ,,,, 0 ,,,, 0 ,,,,-1 ,-1 ,-1 , 0 , 0 , 0 , 0 , 0
BC Design=,, 0 ,, 0 ,,,,,,

Type RM Length L Ch R = 1 ,8805.282,357.184200,357.184200,357.184200
XS GIS Cut Line= 4
689164.207829406715390.020794083688892.879022866715531.701787487
 688663.71235621715532.569843024687999.767125342715953.298673162
#Sta/Elev= 30
9546.752137.13389805.327133.38289860.724133.23379870.724134.29079880.724 134.008
9890.724132.74449900.724128.00279910.725120.98499920.725116.05189930.725113.0508
9960.725 111.0139970.725109.38649990.725104.067810000.73103.757210010.73104.2899
10030.73112.242710050.73 112.08710070.73115.006810092.33129.622210139.68129.0945
10198.88130.661810222.55 130.09910364.62130.776310400.13132.714210423.81 136.222
10471.17137.610510660.59136.671910767.13138.045910778.97136.890610868.04137.4046
#Mann= 3 , 0 , 0
9546.752  0.0465       09546.752  0.0465       010868.04  0.0465       0
#XS Ineff= 2 , 0
       0                               0
Bank Sta=9546.752,10868.04
Exp/Cntr=0.3,0.1

Type RM Length L Ch R = 1 ,8448.098,357.184300,357.184300,357.184300
XS GIS Cut Line= 6
689308.837915777 714558.47624531689064.286871457714712.542374306
688856.402348269714883.600185519 688695.47793494715077.861821474
688525.837930829 715410.92652962687896.138980893715924.975707613
#Sta/Elev= 30
8999.103122.87539131.361124.75719154.992126.09319166.904 128.5059178.816127.8306
 9202.64131.34019226.649132.43029546.065133.66179708.497139.81659864.974138.9346
9909.521137.38099941.975131.6605 9963.46123.02799974.003103.69249984.546 101.853
10005.63101.380910026.73103.757610037.28108.743610048.03111.034110104.12112.3208
10115.81114.992410140.43117.954110153.42126.725310179.41127.931610258.27126.8494
10338.84129.296310365.27 133.17210484.21135.5962 10678.6 134.68711000.86 136.256
#Mann= 3 , 0 , 0
8999.103    0.06       08999.103    0.06       011000.86    0.06       0
#XS Ineff= 2 , 0
       0                               0
Bank Sta=8999.103,11000.86
Exp/Cntr=0.3,0.1

Type RM Length L Ch R = 1 ,8090.914,357.184200,357.184200,357.184200
XS GIS Cut Line= 6
688975.144676044714433.749608848688528.708614119714772.040208461
688379.695101849714951.503697791688091.676546293715421.040030288
687869.611000546715632.805405583687589.123252853715837.383307645
#Sta/Elev= 30
8999.111 126.8439081.603126.79689271.524136.58629469.305144.10499538.134144.7104
9560.592143.13869595.532138.51719701.066128.18819761.628 125.2639844.951126.5442
 9913.85  121.159925.107119.90289945.946114.86959967.725104.38069981.39199.94736
9992.64898.5575810015.2498.8486110026.54101.680810037.85108.034510060.45117.9811
10094.77120.566810106.27122.848510188.45132.147410274.07132.8899 10429.7 132.158
   10580132.860710672.18131.8249 10835.9134.1089 10884.7132.922711000.93133.9452
#Mann= 3 , 0 , 0
8999.111    0.06       08999.111    0.06       011000.93    0.06       0
#XS Ineff= 2 , 0
       0                               0
Bank Sta=8999.111,11000.93
Exp/Cntr=0.3,0.1

Type RM Length L Ch R = 1 ,7733.729,357.184300,357.184300,357.184300
XS GIS Cut Line= 6
688890.665429939714364.549587527688680.923374283714490.694665009
 688302.02199824714743.092177368687911.946768156714956.319582537
687480.377821911715242.187123529687188.105657529715414.805504513
#Sta/Elev= 30
 8999.04125.4899 9214.01135.72319342.507140.43959431.183143.02729503.735142.3441
9538.667140.51759564.196136.0248 9588.38130.18049659.909123.12619753.478119.8737
9878.736119.20559901.207115.97929946.149112.62869957.384109.79299968.619 95.8458
9979.85587.240099991.25185.4477410018.4886.85655 10025.689.0642410037.0798.27064
10048.54109.651910059.34115.067810071.47118.6949 10094.4 121.25910128.81122.6515
10199.45121.969210415.85124.040210524.51123.0695 10620.1123.719411000.96129.3309
#Mann= 3 , 0 , 0
 8999.04  0.0516       0 8999.04  0.0516       011000.96  0.0516       0
#XS Ineff= 2 , 0
       0                               0
Bank Sta=8999.04,11000.96
Exp/Cntr=0.3,0.1

Type RM Length L Ch R = 1 ,7376.545,340.434100,340.434100,340.434100
XS GIS Cut Line= 2
688073.081830621714480.847315893687765.476685703714672.014355078
#Sta/Elev= 30
9871.799124.27959881.314124.25279898.611 123.4679904.862122.79839940.183117.7171
9951.957117.60929955.446114.84959963.731102.42879974.39183.536449975.50482.26865
9987.27877.396669993.33775.681569999.052 74.954810031.2382.0075410034.3783.11599
10046.1583.4903810057.9282.8169710069.1285.2823310081.4790.9709810088.0693.46223
10107.01102.952810116.79 107.02210125.95109.919310140.34112.9053 10144.9113.6956
10152.11114.503210163.89115.512710175.66 116.10710187.43116.223910233.97117.4726
#Mann= 3 , 0 , 0
9871.799    0.12       09871.799    0.12       010233.97    0.12       0
#XS Ineff= 2 , 0
       0                               0
Bank Sta=9871.799,10233.97
Exp/Cntr=0.3,0.1

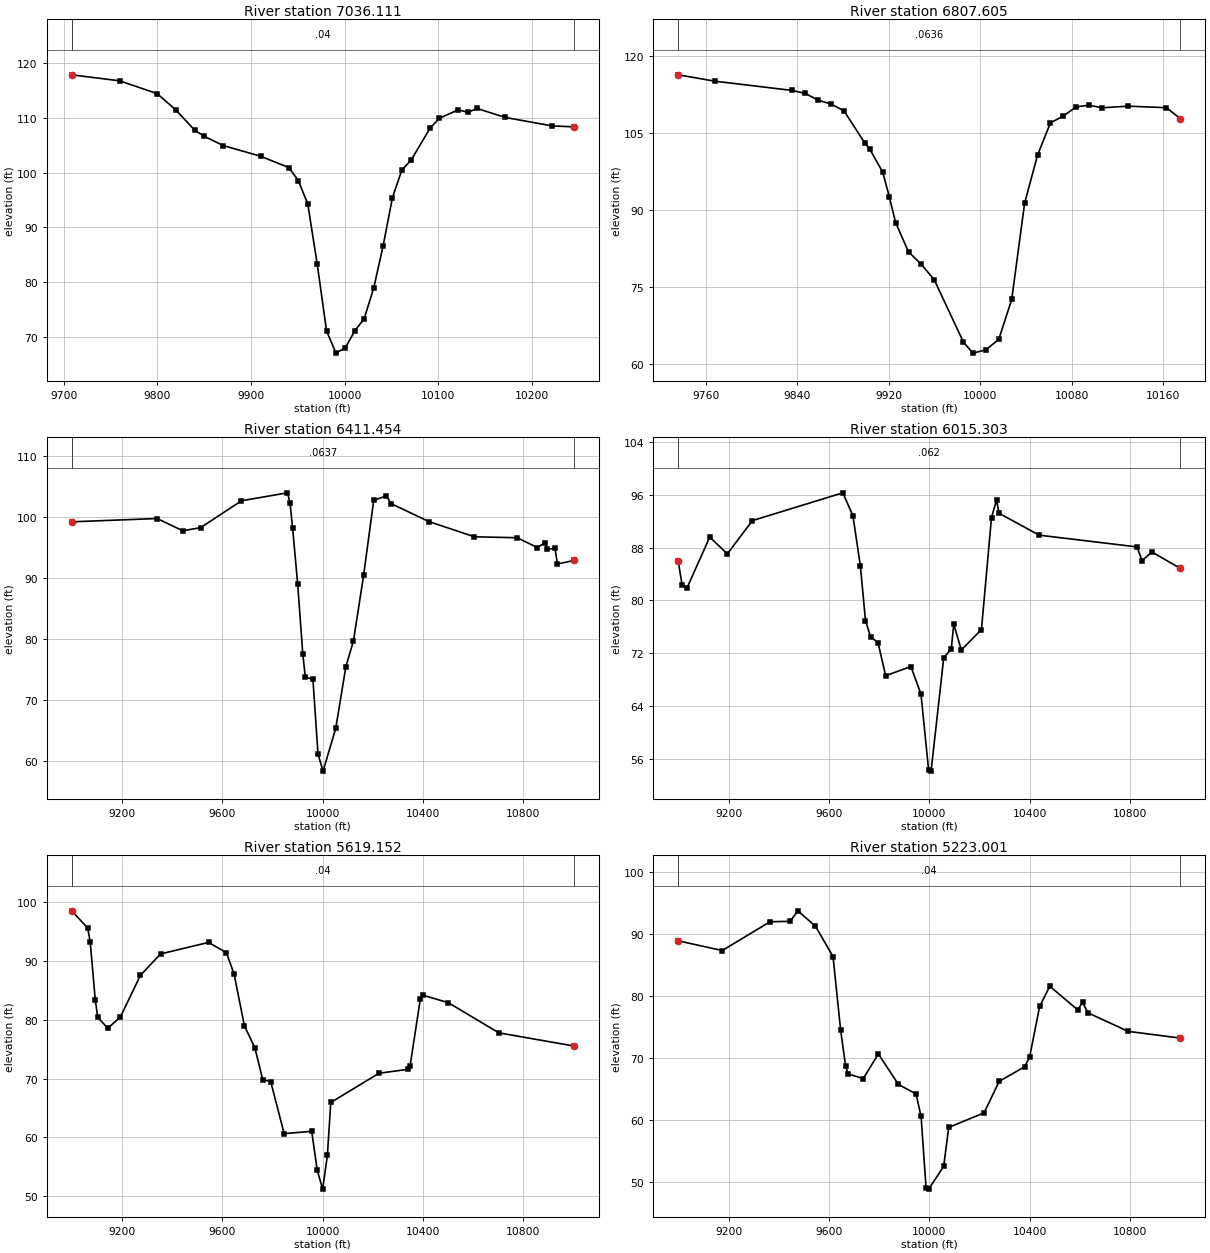
Type RM Length L Ch R = 1 ,7036.111,228.505900,228.505900,228.505900
XS GIS Cut Line= 2
687975.760428846714388.739560634687442.230601251714442.613908038
#Sta/Elev= 30
9708.541117.8959 9759.56116.80249799.763114.45559819.865111.44869839.967107.7412
9850.017106.65939870.119104.96749910.323103.00319940.475100.91979950.52698.55591
9960.57794.293129970.62883.359219980.678 71.05269990.72966.9987510000.7867.98556
10010.8371.0778910020.8873.3068210030.9378.8380810040.9886.5295710051.0395.43946
10061.09100.474810071.14102.337510091.24108.147410101.29109.970410121.39 111.491
10131.44111.036810141.49 111.73810171.64 110.096 10221.9108.550610244.78108.3798
#Mann= 3 , 0 , 0
9708.541    0.04       09708.541    0.04       010244.78    0.04       0
#XS Ineff= 2 , 0
       0                               0
Bank Sta=9708.541,10244.78
Exp/Cntr=0.3,0.1

Type RM Length L Ch R = 1 ,6807.605,396.151100,396.151100,396.151100
XS GIS Cut Line= 2
688003.566543639714350.506152779687614.280936539714147.173938364
#Sta/Elev= 30
9735.938116.24849768.167115.00749835.859113.20329847.141112.61769858.422111.3101
9869.704110.55719880.986109.22589899.029103.0071 9903.55101.76929914.83297.29516
9920.62892.463639926.11487.466619937.39681.779249948.67879.34038 9959.9676.31994
9985.42764.217199993.80662.0823610005.0962.7259810016.3764.7765210027.6572.53429
10038.9391.2583210050.23100.6148 10061.5106.892210072.78108.231210084.06110.0157
10095.34110.331410106.62109.833210129.19110.150310163.03109.850910175.13107.7253
#Mann= 3 , 0 , 0
9735.938  0.0636       09735.938  0.0636       010175.13  0.0636       0
#XS Ineff= 2 , 0
       0                               0
Bank Sta=9735.938,10175.13
Exp/Cntr=0.3,0.1

Type RM Length L Ch R = 1 ,6411.454,396.151000,396.151000,396.151000
XS GIS Cut Line= 6
688749.202894975713654.062592347687933.802570679713814.107003486
687815.499487575713834.375652581687567.979162434713869.409900042
687464.165834213713881.682378424686769.895055531713936.658401824
#Sta/Elev= 30
8999.01499.25586 9339.37 99.79669441.21297.790499512.56898.286189675.762102.7148
9859.201 104.0199869.347102.31159879.49298.272329899.78489.017649920.07577.58846
9930.22173.746699960.60473.375439980.79361.0895410000.9858.2826810051.4965.28952
10091.8975.4329210122.1979.68448 10162.690.4415710202.99102.792810253.34103.5051
10273.48102.218210424.0799.2811110604.6396.7938110775.1696.6378210855.4195.02737
10885.5195.8287910895.5494.7272510925.6394.9240210935.6692.3155711000.9792.90549
#Mann= 3 , 0 , 0
8999.014  0.0637       08999.014  0.0637       011000.97  0.0637       0
#XS Ineff= 2 , 0
       09587.091                       0
Bank Sta=8999.014,11000.97
Exp/Cntr=0.3,0.1

Type RM Length L Ch R = 1 ,6015.303,396.151100,396.151100,396.151100
XS GIS Cut Line= 6
688660.354978981713402.614180926687991.186410879713437.269200112
687590.606221372713480.261708421687392.244452856713494.814829208
687167.988088619713502.640315671 686662.36798534713508.507593269
#Sta/Elev= 30
8999.02185.908339014.40682.330199034.44581.913669124.62189.584119194.758 87.0415
9294.87792.080779655.27896.283919695.40892.84341 9725.5385.138649745.61276.94648
9765.69374.519869795.81573.577559825.976 68.59499926.67869.985689966.95965.80901
9997.16954.3784710007.2454.1501510057.5571.2936910087.6872.66765 10097.776.39392
10127.7872.49014   1020875.5767510248.1192.5455510268.1695.1808810278.1793.19293
10438.2789.8736310828.3388.0938910848.3386.0370810888.3387.3105911000.9784.84724
#Mann= 3 , 0 , 0
8999.021   0.062       08999.021   0.062       011000.97   0.062       0
#XS Ineff= 2 , 0
       09534.685                       0
Bank Sta=8999.021,11000.97
Exp/Cntr=0.3,0.1

Type RM Length L Ch R = 1 ,5619.152,396.151000,396.151000,396.151000
XS GIS Cut Line= 6
688658.591494225713256.249399582 688297.99826733713247.132801758
688060.191402344713215.746206078687892.354121007713170.957116106
687392.417816744 712980.26199936 686707.88221294712887.479248557
#Sta/Elev= 30
8999.086 98.55179062.678 95.61139072.67893.213629092.67883.443559102.67880.42771
9142.67878.574439192.69180.467589272.77187.569429352.89391.215719544.27593.17702
9615.50691.43238 9646.3387.786449687.42978.980849729.07475.248239760.47169.83055
9792.30169.504049845.87660.639869955.66261.037819977.69454.435919999.35851.19795
10018.2356.9347510031.8465.9436210224.1570.9167610337.73  71.57210347.9772.15416
10388.8183.5408210398.9884.2006510500.3982.92109 10702.277.7879411000.9475.55003
#Mann= 3 , 0 , 0
8999.086    0.04       08999.086    0.04       011000.94    0.04       0
#XS Ineff= 2 , 0
       09554.838                       0
Bank Sta=8999.086,11000.94
Exp/Cntr=0.3,0.1

Type RM Length L Ch R = 1 ,5223.001,396.151100,396.151100,396.151100
XS GIS Cut Line= 6
688880.027836363712826.361691906688046.843640195712755.222840601
687927.134101345712748.825251931 687844.51830236 712750.94479851
687765.953733619712745.238565336686888.838455678712632.254377276
#Sta/Elev= 30
 8999.0588.844239174.58687.289659365.19891.920549445.52891.994449475.65293.68187
9545.94191.22008 9616.23 86.32339646.35474.557659666.436 68.64939676.47767.40163
9736.725 66.66059796.97270.63145 9877.1965.705939947.28964.181289967.30560.56741
9987.31249.002979997.31548.8514710057.3852.4988910077.4458.7970710218.3761.13067
10278.8766.21414 10379.768.5505910399.8670.0743510440.1978.3013210480.5281.53465
10591.4377.73861 10611.678.9536810631.7677.2680610793.08  74.26311000.9573.18285
#Mann= 3 , 0 , 0
 8999.05    0.04       0 8999.05    0.04       011000.95    0.04       0
#XS Ineff= 2 , 0
       09834.978                       0
Bank Sta=8999.05,11000.95
Exp/Cntr=0.3,0.1