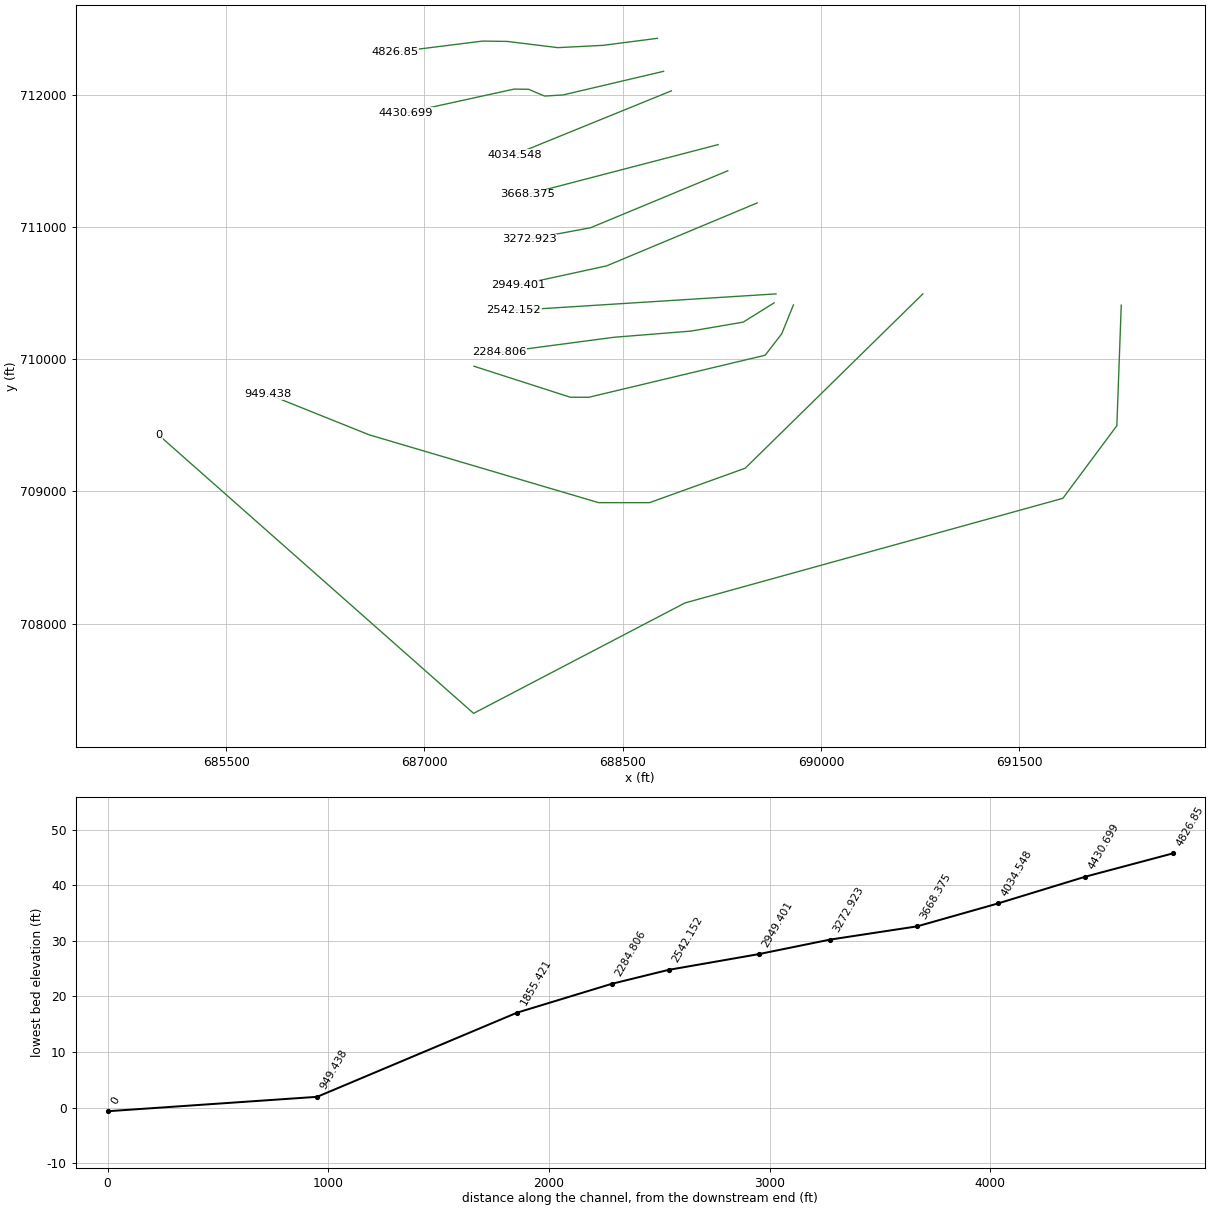
HEC-RAS study 5048_ras.prj: 5048

--- 5048_ras.g01 (geometry) --- (continued)

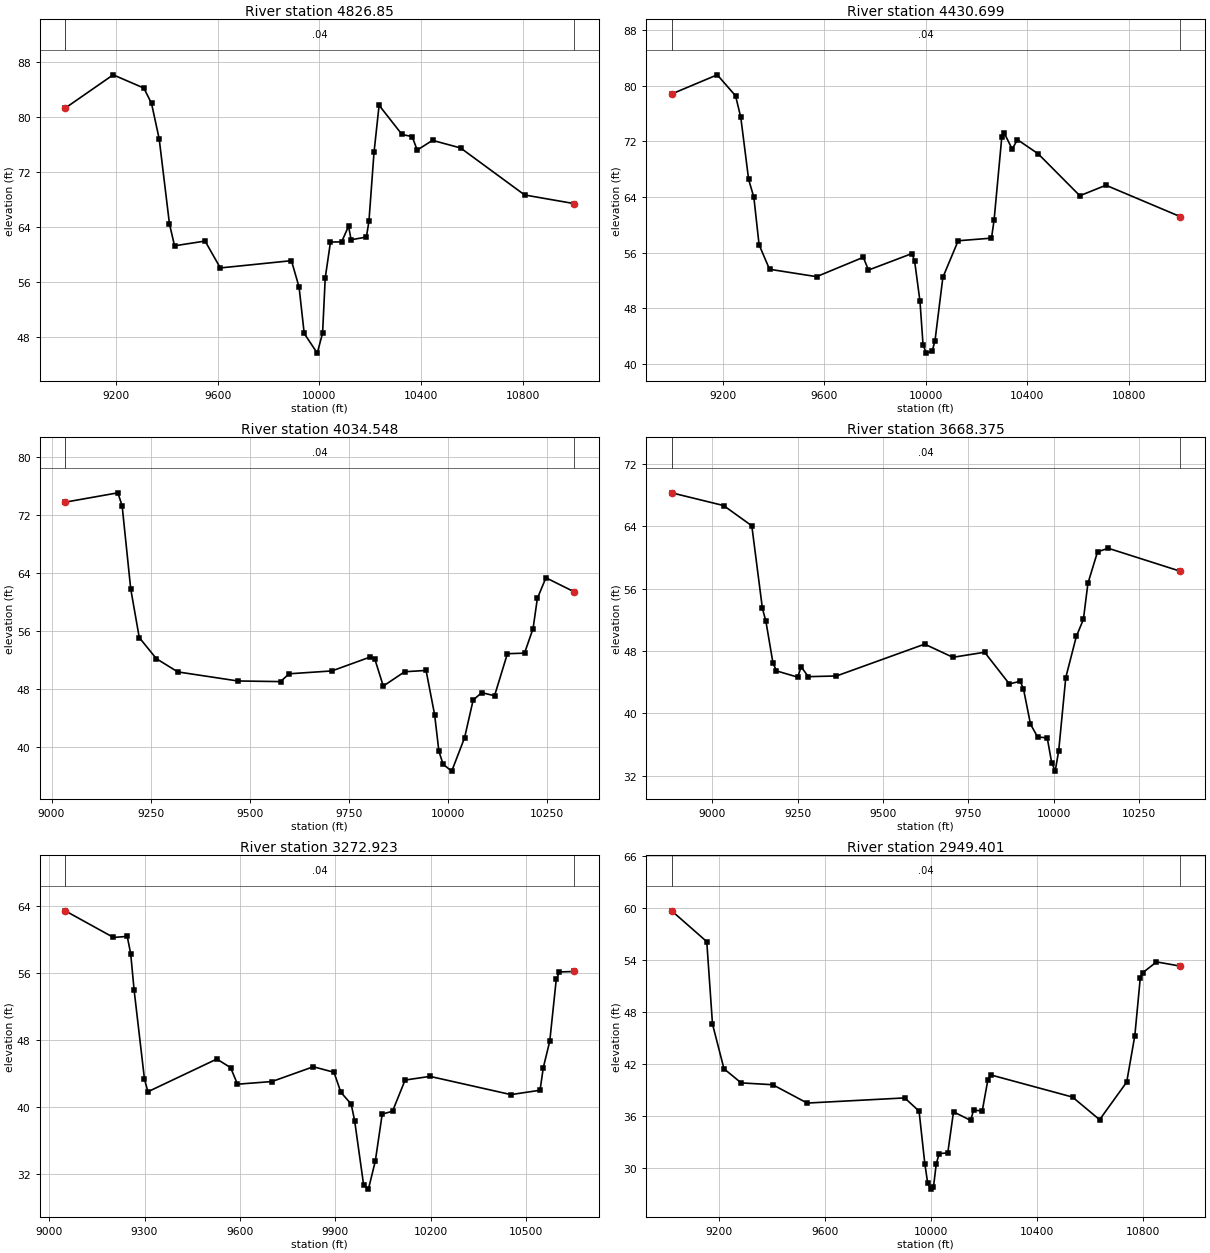
Type RM Length L Ch R = 1 , 4826.85,396.151000,396.151000,396.151000
XS GIS Cut Line= 6
688761.994441272712425.441926511688350.942605891712372.444465755
688009.560690462712355.062387331687627.043859206712402.103713113
 687439.71031065712404.667200187686774.771029536712321.453722243
#Sta/Elev= 30
8999.09681.314969187.97286.152399308.886  84.2289339.07481.991449369.26276.82545
9409.51264.530849429.578 61.3106 9549.8861.999469609.98458.09503 9890.0959.15043
9920.155 55.29539940.295 48.57099991.74345.7179210012.6948.6386510023.1656.67287
10043.7761.8586810087.6561.8793910114.9264.1584210124.9962.1885910185.1662.58267
10195.1864.85019 10215.274.8729410235.2281.7287610325.2377.4905110365.3277.17645
10385.3775.2193610445.5476.6323810556.1775.5261710808.5368.6949911000.9367.45727
#Mann= 3 , 0 , 0
8999.096    0.04       08999.096    0.04       011000.93    0.04       0
#XS Ineff= 2 , 0
       09821.166                       0
Bank Sta=8999.096,11000.93
Exp/Cntr=0.3,0.1

Type RM Length L Ch R = 1 ,4430.699,396.151100,396.151100,396.151100
XS GIS Cut Line= 6
688809.307354282712175.962135543688049.116360957711997.517646908
687909.791280679711989.000246047687787.542035508712040.336020999
687678.740782699712041.764306724686861.133501955711862.692363612
#Sta/Elev= 30
8999.13978.823259178.59581.577489250.662 78.55769271.25375.471659302.13966.52995
 9322.73 63.9602 9343.3257.134779384.502 53.59829569.70252.535789753.74755.32189
9774.11253.485339945.33555.859669955.88354.768239976.979 48.96579988.92942.75278
10001.6541.5337210025.2841.8372510036.17 43.348110067.0652.4387410127.2857.70227
10258.5458.0797910268.6760.6458910299.2872.6995310309.4973.1453110340.1370.88016
10360.5572.2527710442.3870.2118510606.4564.1818910709.1665.6912811000.8461.18991
#Mann= 3 , 0 , 0
8999.139    0.04       08999.139    0.04       011000.84    0.04       0
#XS Ineff= 2 , 0
       09768.621                       0
Bank Sta=8999.139,11000.84
Exp/Cntr=0.3,0.1

Type RM Length L Ch R = 1 ,4034.548,366.172300,366.172300,366.172300
XS GIS Cut Line= 2
688867.984726548712028.314509407687680.484726578711545.675620496
#Sta/Elev= 30
 9034.5273.800899167.27475.089249178.06873.292849199.65761.865899221.24655.13199
9264.42352.221719318.39550.398849469.51749.150869577.46149.061119599.04950.13853
9706.99350.533119804.14352.460929814.93752.238519836.52648.444269890.49850.42061
 9944.4750.601299966.05944.500979976.85339.447269987.64737.6486110009.2436.71889
10041.6241.3280210063.2146.51622 10084.847.5383910117.1847.1140510149.5652.90878
10192.7452.9858310214.3356.3828410225.1260.5231710246.7163.3806310316.3561.48384
#Mann= 3 , 0 , 0
 9034.52    0.04       0 9034.52    0.04       010316.35    0.04       0
#XS Ineff= 2 , 0
       09761.925                       0
Bank Sta=9034.52,10316.35
Exp/Cntr=0.3,0.1

Type RM Length L Ch R = 1 ,3668.375,395.452300,395.452300,395.452300
XS GIS Cut Line= 2
689222.151393205711622.064509407687781.179170996711247.064509407
#Sta/Elev= 30
8881.35768.271959033.40966.641669116.07464.046359147.07353.472239157.40651.79421
9178.07246.456069188.405 45.44419250.404 44.64919260.73745.974899281.40344.70738
9364.06844.795539622.39548.875969705.05947.189939798.05747.836589870.38943.77499
9902.05244.112059911.72143.162819932.38738.618649953.05336.984169981.46436.85224
9994.38633.6899710004.7232.5982510015.0535.2162110035.7244.5944510066.7249.87502
10087.3852.0502210100.5856.6676710128.7260.7018110159.7161.1709410370.3258.23338
#Mann= 3 , 0 , 0
8881.357    0.04       08881.357    0.04       010370.32    0.04       0
#XS Ineff= 2 , 0
       09704.832        10119.27       0
Bank Sta=8881.357,10370.32
Exp/Cntr=0.3,0.1

Type RM Length L Ch R = 1 ,3272.923,323.522300,323.522300,323.522300
XS GIS Cut Line= 3
689295.068059921711424.147842735688256.873615474710993.592287168
687791.595837653710906.786731631
#Sta/Elev= 30
9050.72163.473499202.35760.29298 9245.6660.414479256.48658.351689267.31253.96686
 9299.7943.359599310.61541.851259527.13245.758189570.43644.730259592.08742.75244
9700.34643.070019830.25644.836049895.21144.178129916.86341.78708 9949.3440.37314
9960.166 38.3906 9988.2530.7472110003.4730.2109610025.1233.5610910046.7739.17769
10079.2539.5210910118.7743.2472410196.9143.6852410451.2241.5083610542.7742.02875
10552.9444.7291510573.29  47.89910593.6455.2686210603.8156.1685510647.9656.22206
#Mann= 3 , 0 , 0
9050.721    0.04       09050.721    0.04       010647.96    0.04       0
#XS Ineff= 2 , 0
       09821.262        10221.85       0
Bank Sta=9050.721,10647.96
Exp/Cntr=0.3,0.1

Type RM Length L Ch R = 1 ,2949.401,407.249000,407.249000,407.249000
XS GIS Cut Line= 3
 689517.29028213711181.092287168688378.401393205710705.397842735
687708.262504339710559.564509392
#Sta/Elev= 30
9020.98259.632299153.51156.086399175.18646.596849218.53541.446129283.55839.82382
9402.76839.612699532.81537.501989901.28138.094079955.46836.573339977.14230.53273
9987.97928.299669998.81727.5942910009.6527.7913410020.49 30.512810031.3331.68942
10063.8431.7609710085.5136.4935810150.54 35.503110161.3836.7241810193.8936.56143
10215.5640.21388 10226.440.7402610535.0238.1923910637.3735.5863310739.7139.91277
10770.4145.2640610790.8851.8643610801.1152.5230510852.2853.7533810941.0553.27523
#Mann= 3 , 0 , 0
9020.982    0.04       09020.982    0.04       010941.05    0.04       0
#XS Ineff= 2 , 0
       09900.455        10295.44       0
Bank Sta=9020.982,10941.05
Exp/Cntr=0.3,0.1

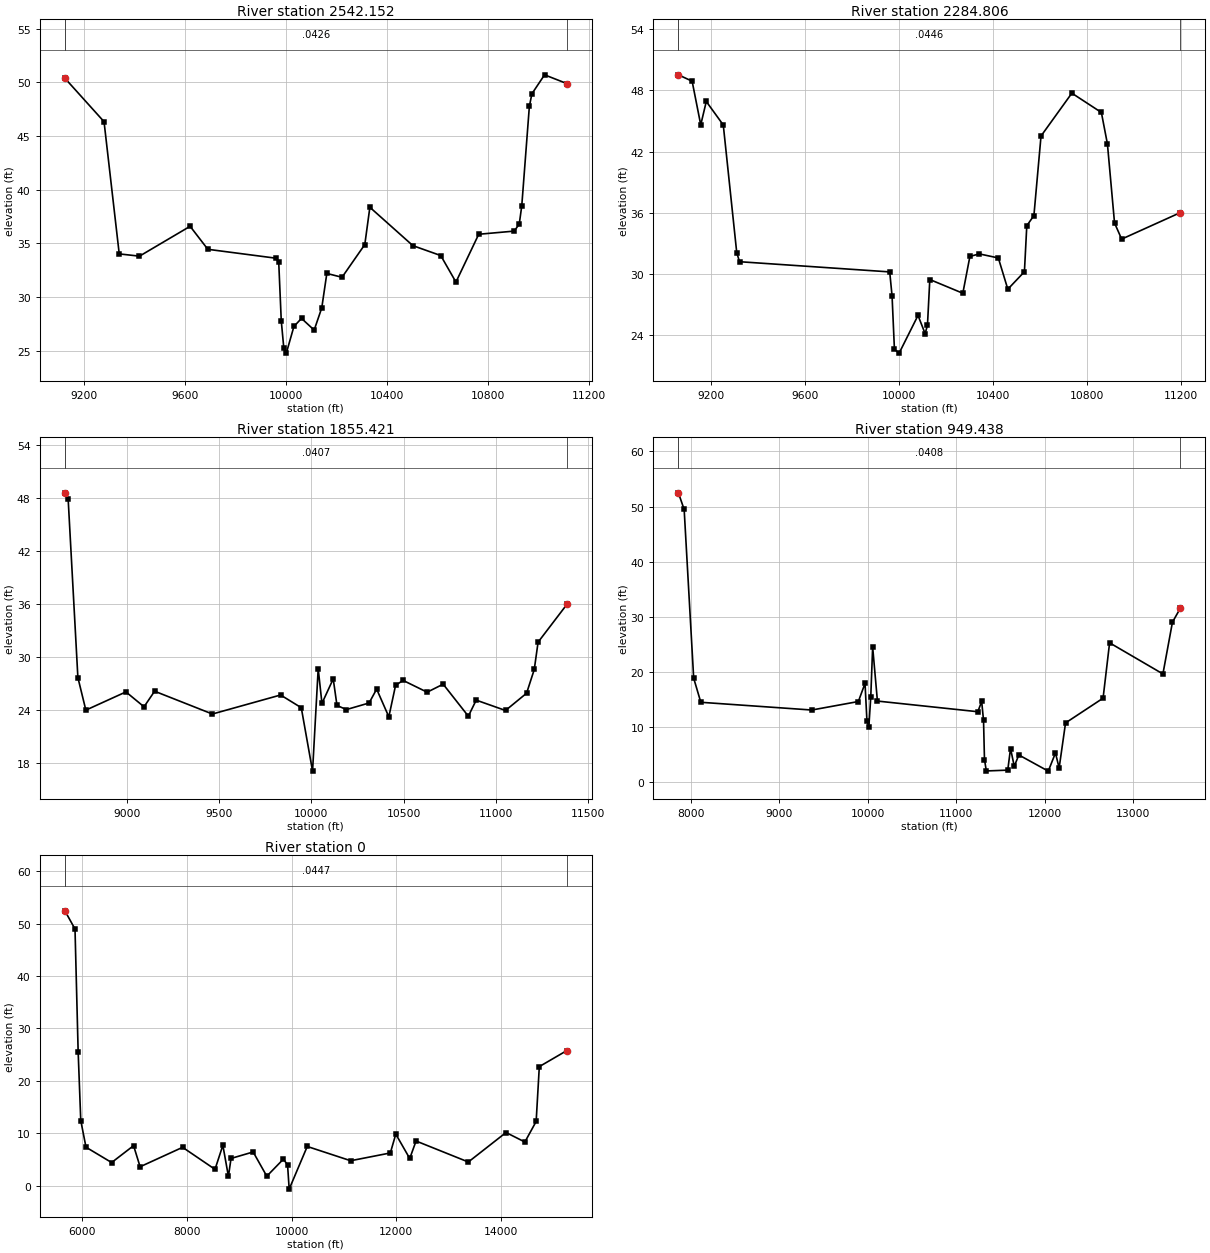
Type RM Length L Ch R = 1 ,2542.152,257.345400,257.345400,257.345400
XS GIS Cut Line= 2
689659.651393205710493.592287168687677.012504339710368.592287168
#Sta/Elev= 30
 9126.2650.390099281.21946.340729341.33834.019859421.49733.809039621.89436.59246
9692.03334.447099962.56933.616089972.58933.250619982.60927.793859992.62825.25102
10002.6524.7724310032.71 27.257910062.77 28.009910112.8726.9188110142.9328.98951
10162.9732.1992810223.0931.8400510313.2634.89037 10333.338.3640410503.64 34.7878
10613.8633.8647110673.9831.3923510764.1635.8497510904.4436.1435810924.4736.79005
10934.49 38.497510964.5547.7647910974.5748.9392611024.6750.7076611112.8449.89388
#Mann= 3 , 0 , 0
 9126.26  0.0426       0 9126.26  0.0426       011112.84  0.0426       0
#XS Ineff= 2 , 0
       09894.263        10401.94       0
Bank Sta=9126.26,11112.84
Exp/Cntr=0.3,0.1

Type RM Length L Ch R = 1 ,2284.806,429.385400,429.385400,429.385400
XS GIS Cut Line= 5
689645.762504339710425.883953854689411.387504339710280.050620496
689015.554170996710212.342287168688432.220837653710165.467287168
687567.637504339710050.883953854
#Sta/Elev= 30
 9061.7349.528179120.18948.90419 9156.85  44.6299180.40646.916179252.68944.61631
9309.96132.111319321.73931.220379960.61930.221769970.65127.856269980.684 22.6331
10000.7522.2646810081.0125.95726 10111.124.1809310121.13 24.973410131.1729.47558
10271.6228.1302510301.7231.7408710341.9431.9844810422.64 31.588610462.9928.52675
 10533.630.2383810543.6934.7453410573.9535.7404810604.2143.5347110735.3547.73134
10860.9245.8420810886.6642.7564810916.9235.0111110947.1933.4342611196.71   36.03
#Mann= 3 , 0 , 0
 9061.73  0.0446       0 9061.73  0.0446       011196.71  0.0446       0
#XS Ineff= 2 , 0
       09681.571        10384.44       0
Bank Sta=9061.73,11196.71
Exp/Cntr=0.3,0.1

Type RM Length L Ch R = 1 ,1855.421,905.983000,905.983000,905.983000
XS GIS Cut Line= 6
689791.595837682710410.258953854689703.054170996710191.508953854
689578.054170996710030.050620496688244.720837653709712.342287183
688104.095837653709712.342287183687374.929170996709946.717287198
#Sta/Elev= 30
8665.27248.594348682.85247.935538735.67427.678038778.82723.982748996.09526.04797
9094.10624.361769151.36526.125639464.37523.543549834.08425.697829946.08324.25724
10007.1717.0754710037.7228.6749110058.0824.7482510119.1727.5197710139.5324.51505
10190.4424.0462110313.4524.7923610354.4626.3667910420.4723.2259510456.9926.79234
10497.5127.3521810628.0826.0149610714.8326.9236610851.2723.2965910893.7925.11667
11052.7423.9437111166.8825.9003111208.3928.5853911229.1431.6810811384.86 35.9478
#Mann= 3 , 0 , 0
8665.272  0.0407       08665.272  0.0407       011384.86  0.0407       0
#XS Ineff= 2 , 0
       09372.895        10488.03       0
Bank Sta=8665.272,11384.86
Exp/Cntr=0.3,0.1

Type RM Length L Ch R = 1 , 949.438,949.438000,949.438000,949.438000
XS GIS Cut Line= 6
690770.762504339710493.592287168689427.012504339709175.883953854
688703.054170996708915.467287183688317.637504339708915.467287183
686581.724344641709428.422303438685812.223689973709736.803816751
#Sta/Elev= 30
7856.66852.486337922.04349.459638029.71618.822188110.39314.441669365.99313.03586
9892.74214.580279968.252 17.88059989.82611.06166 10011.410.0063710032.9715.34339
10054.5524.4849110108.48 14.662911244.0612.7279511287.9414.5869811309.0111.13647
11319.544.04625811340.61  1.968511582.872.11814611614.476.04171111656.612.814288
11708.424.87528212041.251.93718112122.765.237605 12164.2 2.5009312236.7110.69251
 12661.415.1884312735.0225.2425813338.3219.5911113446.0528.9845613535.2231.52814
#Mann= 3 , 0 , 0
7856.668  0.0408       07856.668  0.0408       013535.22  0.0408       0
#XS Ineff= 2 , 0
       09292.569        11020.28       0
Bank Sta=7856.668,13535.22
Exp/Cntr=0.3,0.1

Type RM Length L Ch R = 1 ,       0,0.000000,0.000000,0.000000
XS GIS Cut Line= 6
692271.756441385710408.335133418692238.423108101709497.224022329
691830.089774787   708948.265689688970.999279231 708157.26925461
687372.103663623707322.571244538684993.631441385   709423.265689
#Sta/Elev= 30
5666.64652.43452 5860.1148.96708 5920.1525.566055970.18412.425296070.2517.342456
6560.5784.4152726979.9577.6359077104.5883.6091957917.4037.319265 8536.893.119073
8687.134 7.712558793.2671.7701448843.3445.1989839266.1776.4327279526.9261.811215
9845.0715.0744099924.2553.9473139955.097-0.6561710300.587.48336711130.734.761121
11889.286.24429311993.529.83708312260.195.18878312381.048.52291113380.654.518328
14101.1110.1441914461.348.33252114677.1712.2521714737.5922.7158515263.6825.77289
#Mann= 3 , 0 , 0
5666.646  0.0447       05666.646  0.0447       015263.68  0.0447       0
#XS Ineff= 2 , 0
       08526.634        11239.19       0
Bank Sta=5666.646,15263.68
Exp/Cntr=0.3,0.1